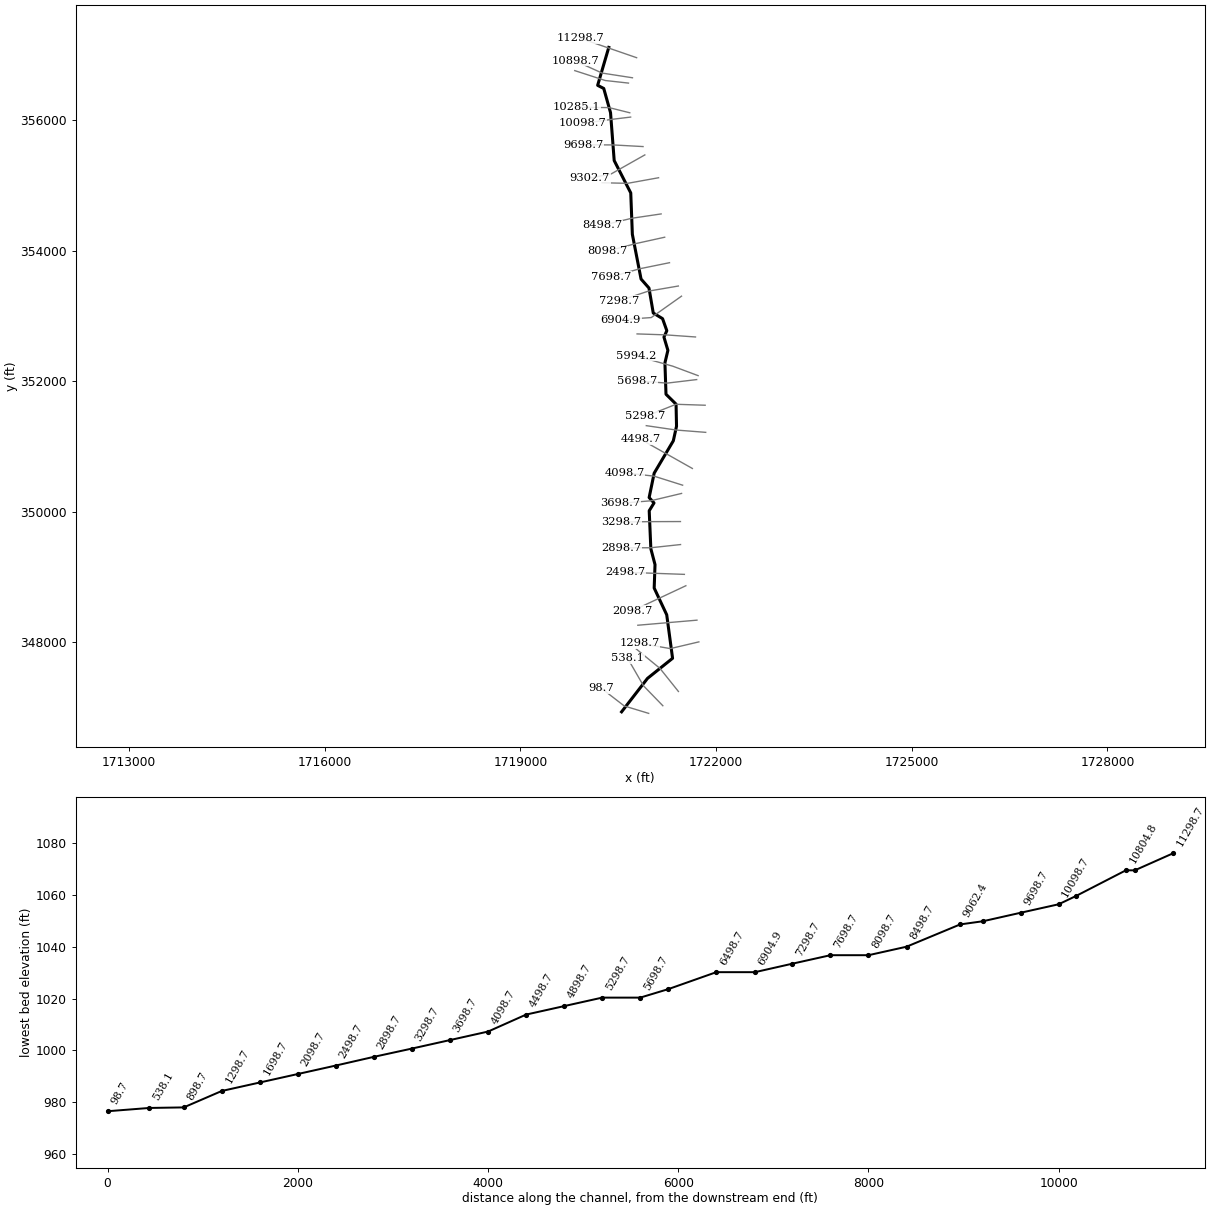
--- BgRn.prj (project) ---

Proj Title=BgRn
Current Plan=p01
Default Exp/Contr=0,0
English Units
Geom File=g01
Flow File=f01
Plan File=p01
BEGIN DESCRIPTION:
END DESCRIPTION:
DSS Export Rating Curves= 0
DSS Export Rating Curve Sorted= 0
DSS Export Volume Flow Curves= 0
DXF OffsetX= 0
DXF OffsetY= 0
DXF ScaleX= 0
DXF ScaleY= 0

--- BgRn.p01 (plan) ---

Plan Title=Floodplain
Program Version=4.00
Geom File=g01
Flow File=f01
K Sum by GR=0
Std Step Tol=0.01
Critical Tol=0.01
Num of Std Step Trials=20
Max Error Tol=0.3
Flow Tol Ratio=0.001
Split Flow NTrial=30
Split Flow Tol=0.02
Split Flow Ratio=0.02
Log Output Level=0
Friction Slope Method=1
Unsteady Friction Slope Method=2
Unsteady Bridges Friction Slope Method=1
Global Log Level=0
CheckData=False
Run HTab=0
Run UNet=0
Run PostProcess=0
UNET Theta=0
UNET Theta Warmup=0
UNET ZTol=0
UNET ZSATol=0
UNET MxIter=0
UNET MaxInSteps=0
UNET DtIC=0
UNET DtMin=0
UNET MaxCRTS=0
UNET WFStab=0
UNET SFStab=0
UNET WFX=0
UNET SFX=0
UNET DSS MLevel=0
UNET DZMax Abort=0
UNET Convert EG Bridges=0
UNET Use Existing IB Tables=0
UNET Froude Limit=0
UNET Froude Power=0
Write IC File=0
Echo Input=False
Echo Output=False
Write Detailed=0

--- BgRn.f01 (steady flow) ---

Flow Title=NFF Regression Equation
Program Version=4.00
Number of Profiles=1
Profile Names=P100yr
River Rch & RM=BgRn,Main      ,11298.7
788.5428
River Rch & RM=BgRn,Main      ,10285.1
866.6811
River Rch & RM=BgRn,Main      ,8498.7
947.4134
River Rch & RM=BgRn,Main      ,8498.7
1109.109
River Rch & RM=BgRn,Main      ,7298.7
1147.045
River Rch & RM=BgRn,Main      ,5698.7
1267.767
River Rch & RM=BgRn,Main      ,98.7
1402.994
River Rch & RM=BgRn,Main      ,98.7
1402.994
Boundary for River Rch & Prof#=BgRn,Main      ,1
Up Type=0
Dn Type=3
Dn Slope=0.007507

--- BgRn.g01 (geometry) ---

Geom Title=USGS 3m DEM
Program Version=4.00

River Reach=BgRn            ,Main
Reach XY= 30
     1720355.643      357111.562     1720184.885      356530.284
     1720278.451      356482.332     1720382.543      356111.577
     1720438.682      355378.254      1720692.48      354882.355
     1720717.041      354248.446     1720850.372      353563.076
     1720972.008      353425.066     1721037.504      353042.616
     1721180.192      352956.067     1721245.688      352771.275
     1721201.244        352674.2     1721262.062      352470.695
     1721216.449      352278.884     1721232.823       351798.19
     1721387.206      351646.145     1721394.224      351308.138
     1721345.102       351084.75     1721051.539      350588.851
     1720974.347      350215.757       1721049.2      350132.717
     1720975.517       350013.42     1721000.524      349431.504
     1721064.589      349188.058     1721051.776      348829.295
      1721243.97      348419.281     1721333.661      347753.008
     1720949.273      347445.497     1720552.071      346932.979

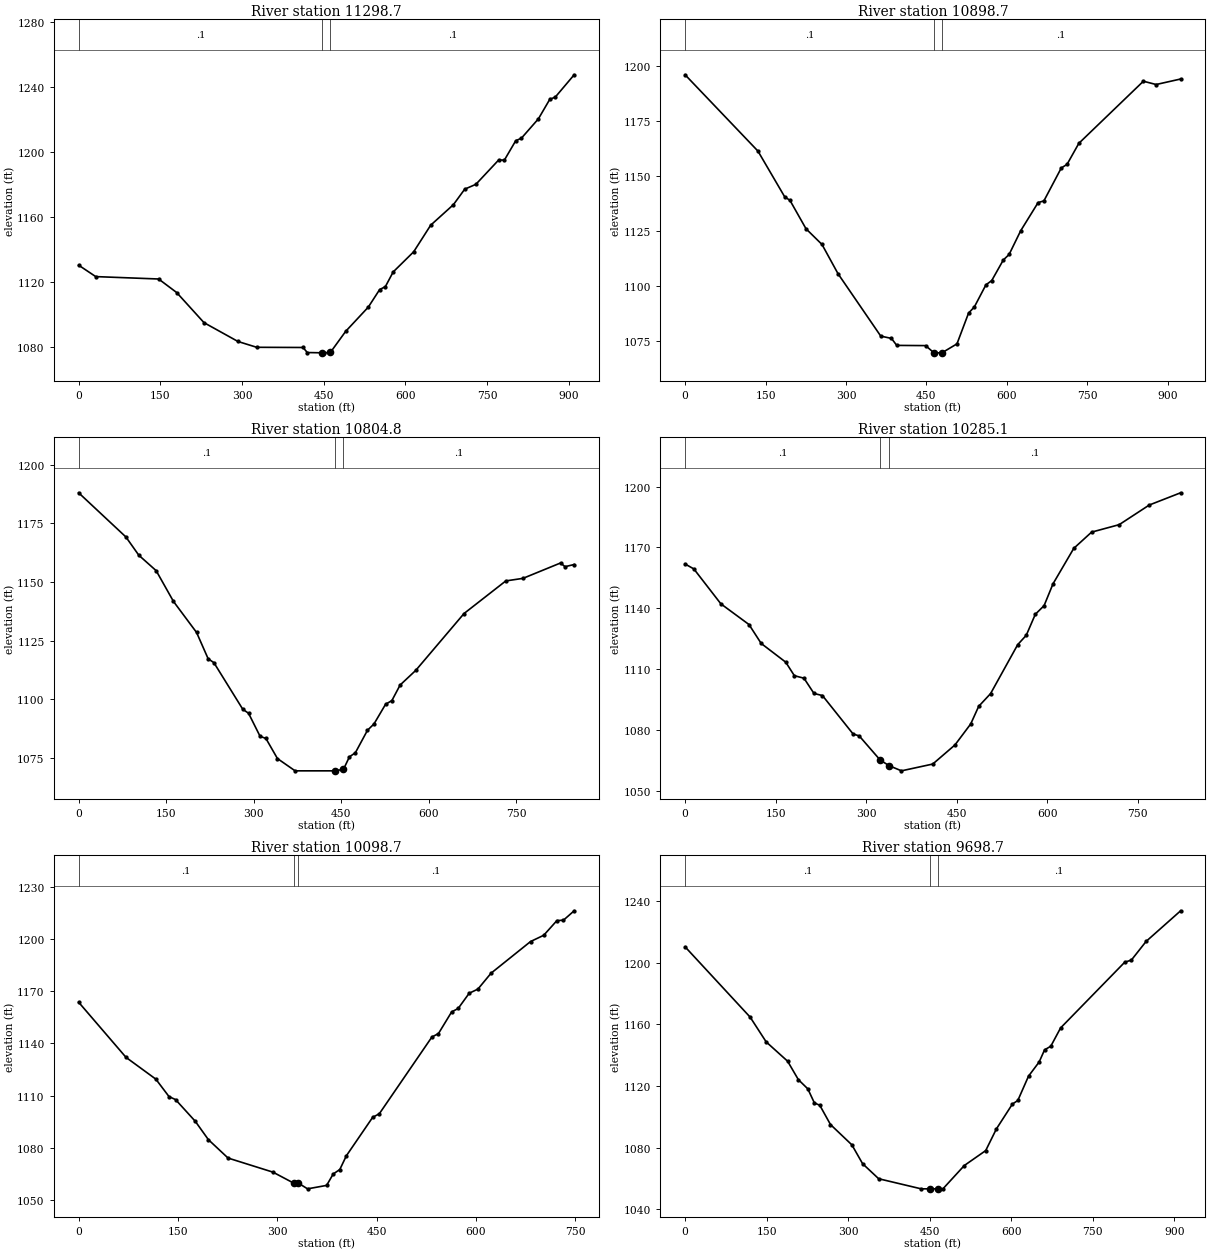
Type RM Length L Ch R = 1 ,11298.7 ,395.76,400,397.876
XS GIS Cut Line= 3
     1720782.528      356953.783     1720352.383      357102.108
     1719922.238      357250.434
#Sta/Elev= 30
       0 1130.18    31.4 1123.13   146.9 1121.65     180 1113.31   230.2 1094.72
   292.6  1083.1     327 1079.51   412.1 1079.39   419.9 1076.27   447.5 1076.11
   450.8 1076.09   462.5 1076.42   490.4 1089.35     532 1104.33   552.8 1115.14
   563.3 1116.94   577.6 1125.99   615.3 1138.45   646.5 1154.85   688.2  1167.5
     709 1177.08   729.5 1180.07   771.4  1195.1   781.8 1194.99   802.7 1206.99
   813.1 1208.53   844.3 1220.47   865.1 1232.45   875.5 1233.96     910 1247.66
#Mann= 3 , 0 , 0
       0      .1       0   447.5    .045       0   462.5      .1       0
Bank Sta=447.5,462.5
XS Rating Curve= 0 ,0
Exp/Cntr=0.3,0.1

Type RM Length L Ch R = 1 ,10898.7 ,97.71,93.863,96.38
XS GIS Cut Line= 3
     1720718.844       356646.34     1720252.986       356718.42
     1719840.524      356905.093
#Sta/Elev= 30
       0 1195.82   135.8 1161.18   185.6 1140.45   195.6 1138.77   225.5 1125.88
   255.3 1118.76   285.2 1105.47   364.9 1077.14   384.8 1076.11   394.7 1072.93
   448.6 1072.83   463.9 1069.58   464.4 1069.55   478.9 1069.55     507 1073.63
   528.6 1087.59   539.4 1090.39     561 1100.43   571.8 1102.36   593.4 1111.71
   604.2 1114.21   625.8 1124.98   658.3 1137.78   669.1 1138.55   701.5 1153.49
   712.3 1155.15   734.3  1164.7   854.6 1192.89   878.4  1191.4   924.1  1193.9
#Mann= 3 , 0 , 0
       0      .1       0   463.9    .045       0   478.9      .1       0
Bank Sta=463.9,478.9
XS Rating Curve= 0 ,0
Exp/Cntr=0.3,0.1

Type RM Length L Ch R = 1 ,10804.8 ,513.013,519.704,527.875
XS GIS Cut Line= 3
     1720657.658      356564.864     1720301.753      356604.409
     1719833.805      356755.998
#Sta/Elev= 30
       0 1188.04      81 1169.22   103.2 1161.42   132.9 1154.85   162.6 1141.73
   202.2 1128.51     222 1117.32   231.9 1115.64   281.4 1095.79   291.3 1094.08
   311.1 1084.24     321 1083.37   340.8 1074.79   371.1 1069.55     439 1069.55
     454 1070.18   464.2 1075.51   474.4 1077.26   495.2 1086.85   506.3 1089.52
   526.2 1097.92     537 1099.49   551.1 1106.11   577.9 1112.35   660.7 1136.59
   732.3 1150.48   761.7 1151.57   826.2 1158.13   833.8 1156.55   849.5 1157.47
#Mann= 3 , 0 , 0
       0      .1       0     439    .045       0     454      .1       0
Bank Sta=439,454
XS Rating Curve= 0 ,0
Exp/Cntr=0.3,0.1

Type RM Length L Ch R = 1 ,10285.1 ,178.822,186.433,189.874
XS GIS Cut Line= 3
      1720677.43      356110.097     1720361.071      356189.187
      1719866.37      356195.179
#Sta/Elev= 30
       0 1161.79    14.5 1159.37    59.3 1142.12   105.8 1131.93   126.1 1122.57
   166.7 1113.34     181 1106.67   196.9 1105.43   213.5 1097.89   227.5 1096.87
   278.3 1077.89   288.4 1076.95   323.2 1065.01   338.2 1062.22   358.4 1059.71
   410.2 1063.06     447 1072.49   473.1 1082.86   486.3 1091.54     506 1097.83
   550.9 1121.98   565.1 1126.62   580.1 1136.98   594.6 1141.23   609.4 1152.01
   643.8 1169.52   673.3 1177.53     719 1181.21   768.8  1190.9   820.8 1196.95
#Mann= 3 , 0 , 0
       0      .1       0   323.2    .045       0   338.2      .1       0
Bank Sta=323.2,338.2
XS Rating Curve= 0 ,0
Exp/Cntr=0.3,0.1

Type RM Length L Ch R = 1 ,10098.7 ,404.122,400,396.618
XS GIS Cut Line= 3
     1720690.612      356044.189     1720399.248      356008.891
      1719948.63      355945.902
#Sta/Elev= 30
       0 1163.72    71.6    1132   116.6  1119.5   136.5 1109.47   146.4 1107.73
   176.2 1095.26     196  1084.7   225.7 1074.13   293.5 1066.03   324.9 1059.71
   331.9 1059.71   345.8 1056.43   374.6 1058.41   384.5 1064.96   394.5 1067.54
   404.4 1075.43   444.2 1097.58   454.1 1099.55   533.6 1143.71   543.5 1145.69
   563.4 1158.13   573.3 1160.13   589.9 1168.86   603.1 1171.26     623 1180.41
   682.6 1198.59   702.5  1202.2   722.4 1210.63   732.3 1210.87   748.5 1216.28
#Mann= 3 , 0 , 0
       0      .1       0   324.9    .045       0   331.9      .1       0
Bank Sta=324.9,331.9
XS Rating Curve= 0 ,0
Exp/Cntr=0.3,0.1

Type RM Length L Ch R = 1 ,9698.7  ,383.036,395.937,407.686
XS GIS Cut Line= 3
     1720881.198       355592.31     1720424.124      355617.514
      1719970.09      355619.632
#Sta/Elev= 30
       0 1210.38   119.7  1164.7   149.2 1148.61   188.6 1136.08   208.4 1124.09
   225.8 1118.11   237.9 1108.95   247.8 1107.45   267.5 1094.93   306.9 1081.71
   326.6 1069.48   356.2 1059.71   434.4 1053.15   450.3 1053.15   465.3 1053.15
   474.4 1053.15   513.8 1068.31   553.1 1077.99   572.8 1092.09   602.3 1108.25
   612.2 1110.55   631.9 1126.35   651.5 1135.58   661.4 1143.43   672.9 1145.81
   690.9 1157.68     809 1200.41   821.1 1201.75   848.3 1213.91   911.8  1233.8
#Mann= 3 , 0 , 0
       0      .1       0   450.3    .045       0   465.3      .1       0
Bank Sta=450.3,465.3
XS Rating Curve= 0 ,0
Exp/Cntr=0.3,0.1

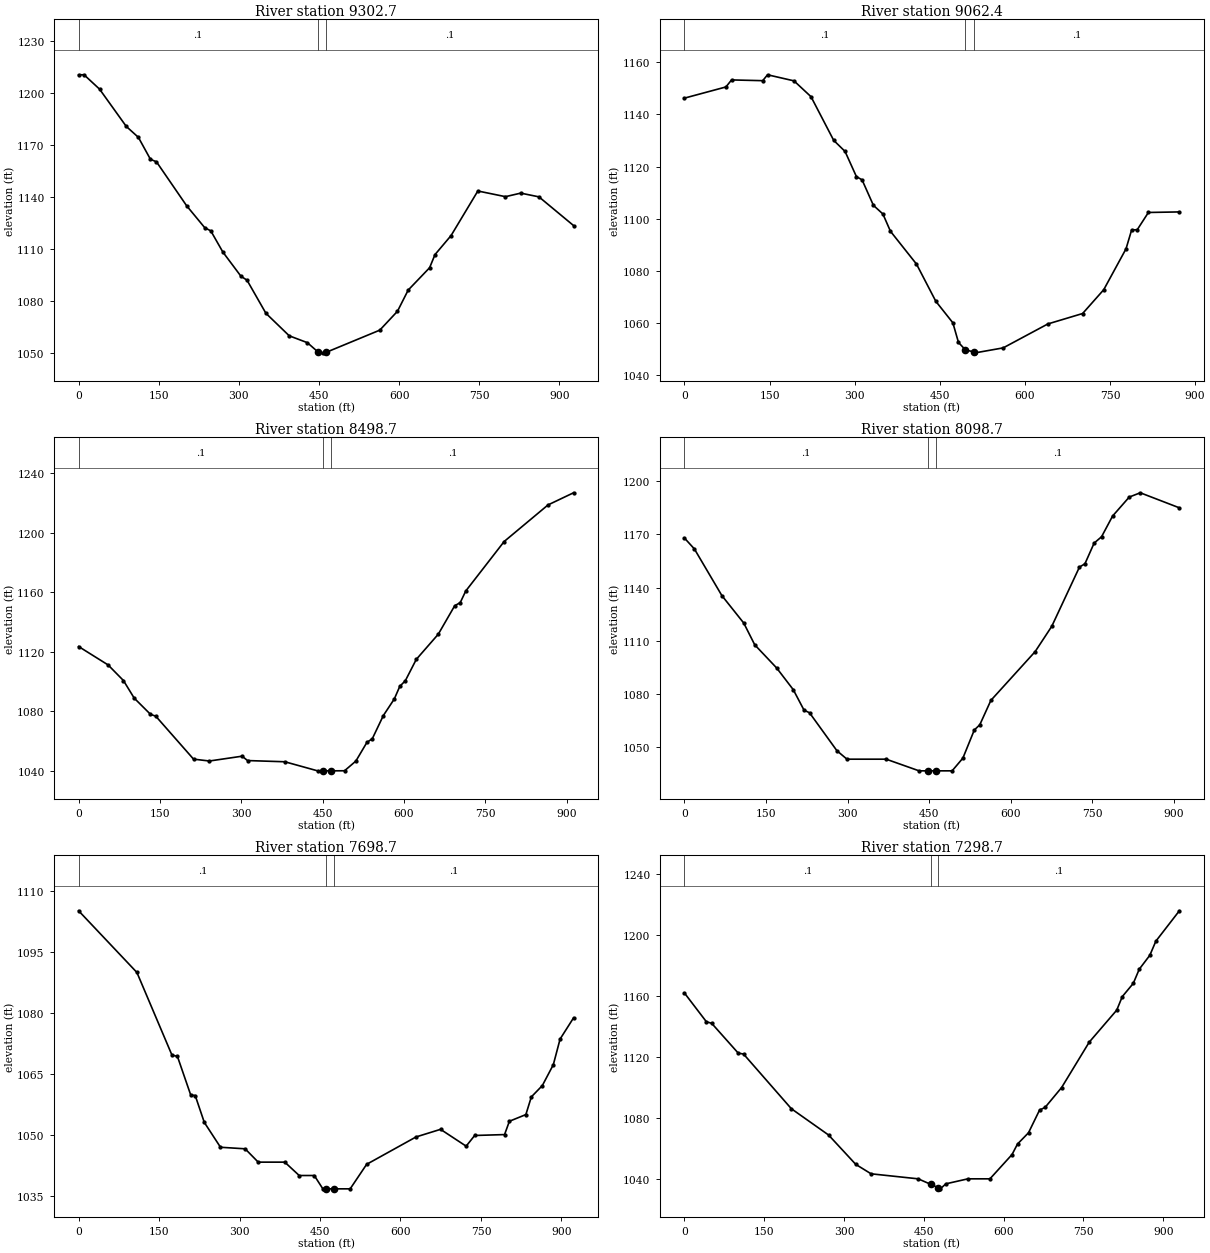
Type RM Length L Ch R = 1 ,9302.7  ,252.203,240.329,227.501
XS GIS Cut Line= 3
     1720908.389      355464.585     1720394.025      355174.201
     1720064.484      355108.292
#Sta/Elev= 30
       0 1210.63    10.2 1210.63    39.2 1202.34    89.3 1180.76   111.9 1174.47
   134.5 1161.77   145.8 1160.31   202.3 1134.89   236.2 1122.21   247.5 1120.39
   270.1 1108.14     304 1094.14   315.3 1091.88   350.7 1072.74   394.4 1059.71
   428.3 1055.75     448 1050.44   458.1 1049.87     463  1050.1   563.9 1062.99
     597  1073.9   617.1 1086.16   657.2 1099.08   667.3 1106.68   697.4 1117.68
   747.5 1143.44   799.2 1140.16   827.8 1142.21   861.9 1140.05   926.7 1123.46
#Mann= 3 , 0 , 0
       0      .1       0     448    .045       0     463      .1       0
Bank Sta=448,463
XS Rating Curve= 0 ,0
Exp/Cntr=0.3,0.1

Type RM Length L Ch R = 1 ,9062.4  ,560.489,563.734,570.038
XS GIS Cut Line= 3
     1721119.015      355114.883     1720644.476      355029.203
     1720254.445      355037.904
#Sta/Elev= 30
       0 1146.24    73.1 1150.52    83.1 1153.22     138 1152.93   146.5 1155.19
   193.1 1152.86   223.1 1146.79   263.1 1130.06   283.1 1125.82   303.1 1116.18
   313.1 1114.92   333.1 1105.15   349.8 1101.85   363.1 1095.23     409 1082.65
   443.1 1068.38   473.1 1060.15     483 1052.62   495.1 1049.81   510.1 1048.97
   512.6 1048.64   561.8 1050.54   640.5 1059.71   701.8 1063.71     739 1072.83
   778.3 1088.51   788.2 1095.75     798  1095.8   817.7 1102.43   872.3 1102.64
#Mann= 3 , 0 , 0
       0      .1       0   495.1    .045       0   510.1      .1       0
Bank Sta=495.1,510.1
XS Rating Curve= 0 ,0
Exp/Cntr=0.3,0.1

Type RM Length L Ch R = 1 ,8498.7  ,398.203,400,400.637
XS GIS Cut Line= 3
     1721158.439      354560.592     1720705.177      354493.587
     1720263.433      354385.638
#Sta/Elev= 30
       0 1123.62    54.4 1111.23    82.7 1100.74   102.6  1088.9   132.5 1078.05
   142.4 1076.75     212 1047.89   241.2 1046.63   301.6 1049.87   311.6 1046.93
   380.4 1046.12   440.8 1040.02   450.7 1040.02   465.7 1040.02   490.5 1040.07
   511.4 1046.59   531.7 1059.11   541.8 1061.68   562.1 1077.21   582.3 1088.36
   592.4 1096.83   602.6 1100.59   622.8 1114.95   663.4  1131.9   693.7 1151.04
   703.9 1153.13     714  1160.9   784.9 1194.22   865.8 1218.82   912.9 1226.99
#Mann= 3 , 0 , 0
       0      .1       0   450.7    .045       0   465.7      .1       0
Bank Sta=450.7,465.7
XS Rating Curve= 0 ,0
Exp/Cntr=0.3,0.1

Type RM Length L Ch R = 1 ,8098.7  ,400.8,400,400.032
XS GIS Cut Line= 3
     1721212.718      354203.667     1720768.473      354105.724
     1720328.176      353989.074
#Sta/Elev= 30
       0 1167.96    18.3 1161.82    68.9 1135.51   109.2 1120.01   129.3 1107.79
   169.6 1094.74   200.2 1082.49     220 1070.95   230.1 1069.47   280.5 1048.08
     299 1043.31   371.1 1043.31   431.6 1036.74   447.4 1036.74   462.4 1036.74
   492.4 1036.74   512.2  1043.9   533.2 1059.76   543.3 1062.69   563.7 1076.45
   645.1 1103.93   675.7  1118.2   726.6 1151.57   736.7 1153.45   753.6 1165.09
   767.3 1168.69   787.6 1180.36   818.2 1191.05   838.5 1193.46   910.4 1184.98
#Mann= 3 , 0 , 0
       0      .1       0   447.4    .045       0   462.4      .1       0
Bank Sta=447.4,462.4
XS Rating Curve= 0 ,0
Exp/Cntr=0.3,0.1

Type RM Length L Ch R = 1 ,7698.7  ,399.086,400,403.309
XS GIS Cut Line= 3
     1721286.554      353813.367     1720827.173      353719.898
     1720390.839      353595.054
#Sta/Elev= 30
       0 1105.16   108.7 1089.98   174.1 1069.62   184.1 1069.37     209 1059.83
   217.4 1059.69   234.3 1053.09   264.5 1046.97   310.4 1046.59   334.8 1043.31
   384.3 1043.31   411.2 1040.02   439.3 1040.02   455.3 1036.74   461.3 1036.74
   476.3 1036.74   506.2 1036.74   536.9 1042.77     629 1049.51   674.7 1051.38
   722.4 1047.24   738.3 1049.87     794 1050.09     803 1053.37   833.7 1055.01
   843.9 1059.36   864.4 1062.15   884.9 1067.29   897.5  1073.6   922.6 1078.81
#Mann= 3 , 0 , 0
       0      .1       0   461.3    .045       0   476.3      .1       0
Bank Sta=461.3,476.3
XS Rating Curve= 0 ,0
Exp/Cntr=0.3,0.1

Type RM Length L Ch R = 1 ,7298.7  ,382.43,393.738,400.479
XS GIS Cut Line= 3
     1721422.302      353456.201     1720959.036       353376.64
     1720522.034      353232.412
#Sta/Elev= 30
       0 1161.83    41.3 1142.96    51.2 1141.97   101.2 1122.39   111.1 1121.82
     201 1085.96   270.9 1068.75     322  1049.5   350.8 1043.31   439.3 1040.02
   462.5 1036.49   477.5 1034.11     481 1033.46   491.3 1036.74   532.8 1040.02
   574.2 1040.02   615.7 1055.93     626 1062.83   646.7 1070.22   667.5 1085.13
   677.8 1086.81   708.9 1099.86   760.7 1129.57   812.5 1150.59   822.9 1159.45
   843.6 1168.14   854.8 1177.42   874.7 1186.55     886 1195.78   930.2 1215.71
#Mann= 3 , 0 , 0
       0      .1       0   462.5    .045       0   477.5      .1       0
Bank Sta=462.5,477.5
XS Rating Curve= 0 ,0
Exp/Cntr=0.3,0.1

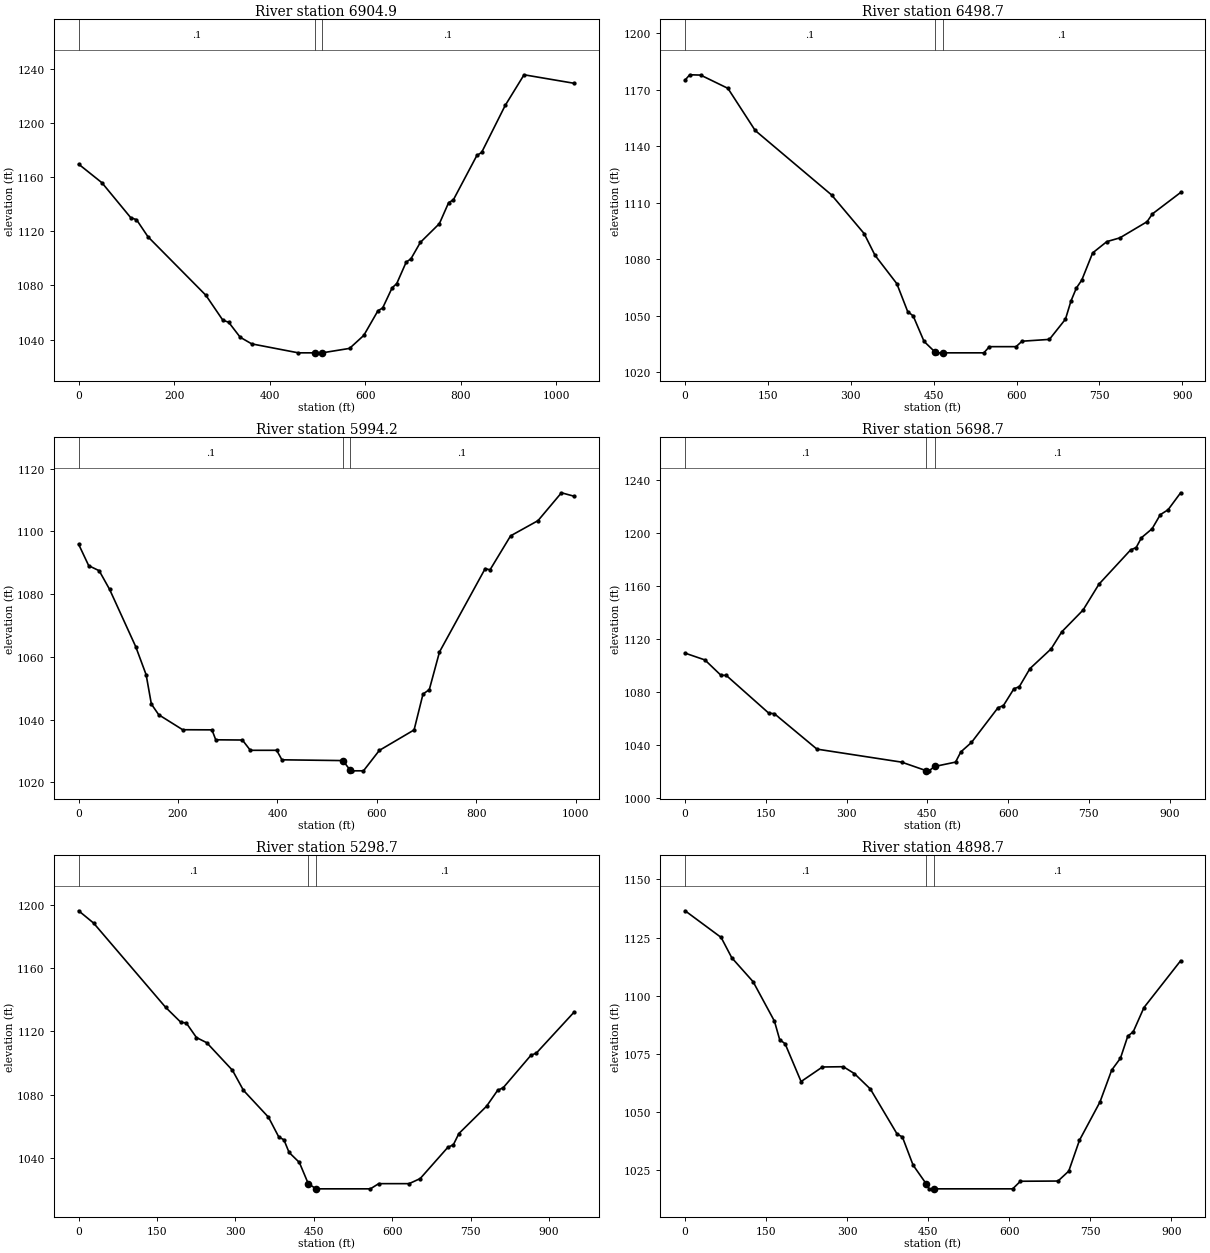
Type RM Length L Ch R = 1 ,6904.9  ,421.528,406.262,392.224
XS GIS Cut Line= 3
     1721470.713      353300.764     1721006.971      352972.866
     1720539.023      352939.912
#Sta/Elev= 30
       0 1169.62    48.8 1155.86   109.1 1130.03   121.1 1128.58   145.2 1115.92
   266.3 1072.72   301.9 1054.26     314  1052.8   338.1 1041.71   362.2 1036.81
   459.8 1030.18   494.7 1030.18   509.7 1030.18     567 1033.46   596.8 1043.07
   626.4 1061.26   636.3 1063.34     656 1078.15   665.8 1081.39   685.6 1097.26
   695.4  1099.6   715.2  1111.8     755 1125.64   774.4 1141.19   784.2 1143.18
   833.5 1176.05   843.4 1178.25   892.7 1212.96   932.2 1235.64  1037.1 1229.34
#Mann= 3 , 0 , 0
       0      .1       0   494.7    .045       0   509.7      .1       0
Bank Sta=494.7,509.7
XS Rating Curve= 0 ,0
Exp/Cntr=0.3,0.1

Type RM Length L Ch R = 1 ,6498.7  ,507.47,504.506,496.257
XS GIS Cut Line= 3
     1721685.226      352675.466      1721226.71       352707.88
     1720789.474      352722.415
#Sta/Elev= 30
       0 1175.02     8.4 1177.82    28.1 1177.66    77.5 1170.62   126.9 1148.24
   265.1 1114.04   324.1 1093.51   343.8 1081.98   383.3 1066.91     403 1052.06
   412.9 1049.79   432.6 1036.25   452.2 1030.68   455.6 1030.18   467.2 1030.18
   540.9 1030.18   550.8 1033.46   599.2 1033.46   609.9 1036.35   659.5 1037.32
   688.6 1048.06   698.5 1057.64   708.3 1064.56   718.2 1068.85   737.8 1083.23
   763.5 1089.24   787.1 1091.23   836.3  1099.8   846.1 1103.98   897.1 1115.33
#Mann= 3 , 0 , 0
       0      .1       0   452.2    .045       0   467.2      .1       0
Bank Sta=452.2,467.2
XS Rating Curve= 0 ,0
Exp/Cntr=0.3,0.1

Type RM Length L Ch R = 1 ,5994.2  ,286.402,295.494,300.209
XS GIS Cut Line= 3
     1721725.371      352083.105     1721336.513      352228.103
     1720776.425      352385.379
#Sta/Elev= 30
       0 1095.89    20.3 1089.05    41.3 1087.46    62.3  1081.5   114.8 1063.25
   135.8 1054.27   146.3 1044.93   161.1 1041.52   209.3 1036.74   268.2  1036.7
   275.8 1033.53   329.4 1033.46   345.4 1030.18   398.4 1030.18   408.9 1027.15
   531.6  1026.9   546.6 1023.76   549.1 1023.63     573 1023.64   604.9 1030.15
   674.8 1036.68   692.7 1048.11   705.4 1049.54   725.9 1061.55   817.8 1088.13
   827.5 1087.73   868.9 1098.57   924.1 1103.43   971.2 1112.31   996.8  1111.2
#Mann= 3 , 0 , 0
       0      .1       0   531.6    .045       0   546.6      .1       0
Bank Sta=531.6,546.6
XS Rating Curve= 0 ,0
Exp/Cntr=0.3,0.1

Type RM Length L Ch R = 1 ,5698.7  ,404.881,400,408.35
XS GIS Cut Line= 3
     1721703.526      352022.885     1721250.825      351968.617
     1720787.497      352003.001
#Sta/Elev= 30
       0 1109.22    36.8 1104.09    66.5 1092.52    76.4 1092.43   155.7  1063.8
   165.6 1063.55   244.9 1036.74   402.4  1026.9   448.4 1020.39     453 1020.34
   463.4 1023.62   502.4 1026.94   512.2 1034.64     532 1041.79   581.3 1068.05
   591.2 1069.56   610.9 1082.36   620.8 1083.87   640.5 1097.51     680 1112.48
   699.7 1125.31   739.2 1141.73   768.8 1161.31   827.6 1187.16   837.9 1188.97
   847.7 1196.37   867.5 1203.15   882.7 1213.76   897.1 1217.46   920.5 1230.31
#Mann= 3 , 0 , 0
       0      .1       0   448.4    .045       0   463.4      .1       0
Bank Sta=448.4,463.4
XS Rating Curve= 0 ,0
Exp/Cntr=0.3,0.1

Type RM Length L Ch R = 1 ,5298.7  ,400.91,400,385.284
XS GIS Cut Line= 3
     1721833.353      351629.874     1721386.657      351644.497
     1720920.864      351458.956
#Sta/Elev= 30
       0 1196.21    28.6 1188.45   166.4 1135.17     196 1125.55   205.8 1125.33
   225.5 1116.02   245.2 1112.76   294.4 1095.32   315.4 1082.65   363.3 1065.65
     383 1053.15   392.9 1051.34   402.7 1043.38   422.4 1037.03   439.4 1023.65
   454.4 1020.35     455 1020.34   558.3 1020.34   574.3 1023.62   632.4 1023.62
   653.6 1026.82   706.5 1046.59   717.1 1048.23   727.7 1055.32   780.7 1072.62
   801.9 1082.68   812.5 1084.29   865.4 1104.76     876 1106.23   948.3 1132.17
#Mann= 3 , 0 , 0
       0      .1       0   439.4    .045       0   454.4      .1       0
Bank Sta=439.4,454.4
XS Rating Curve= 0 ,0
Exp/Cntr=0.3,0.1

Type RM Length L Ch R = 1 ,4898.7  ,409.802,400,391.712
XS GIS Cut Line= 3
     1721841.722      351214.469     1721389.665      351249.787
     1720930.669      351316.878
#Sta/Elev= 30
       0  1136.5    66.7 1125.05    86.4 1116.32   125.9 1106.03   165.4 1089.08
   175.1 1081.12   185.1  1079.4   214.7 1063.14   254.2  1069.4   292.9 1069.52
   313.4 1066.56     343 1059.92   392.4 1040.62   402.3 1039.31     422 1027.27
   445.9 1019.35   451.6 1017.06   460.9 1017.06   606.4 1017.06   620.7 1020.32
   690.3 1020.41   710.2 1024.68     730 1037.92     768 1054.38   789.7 1068.08
   805.9 1073.18   819.5 1082.68   829.5  1084.5   849.4 1094.93   917.3 1115.04
#Mann= 3 , 0 , 0
       0      .1       0   445.9    .045       0   460.9      .1       0
Bank Sta=445.9,460.9
XS Rating Curve= 0 ,0
Exp/Cntr=0.3,0.1

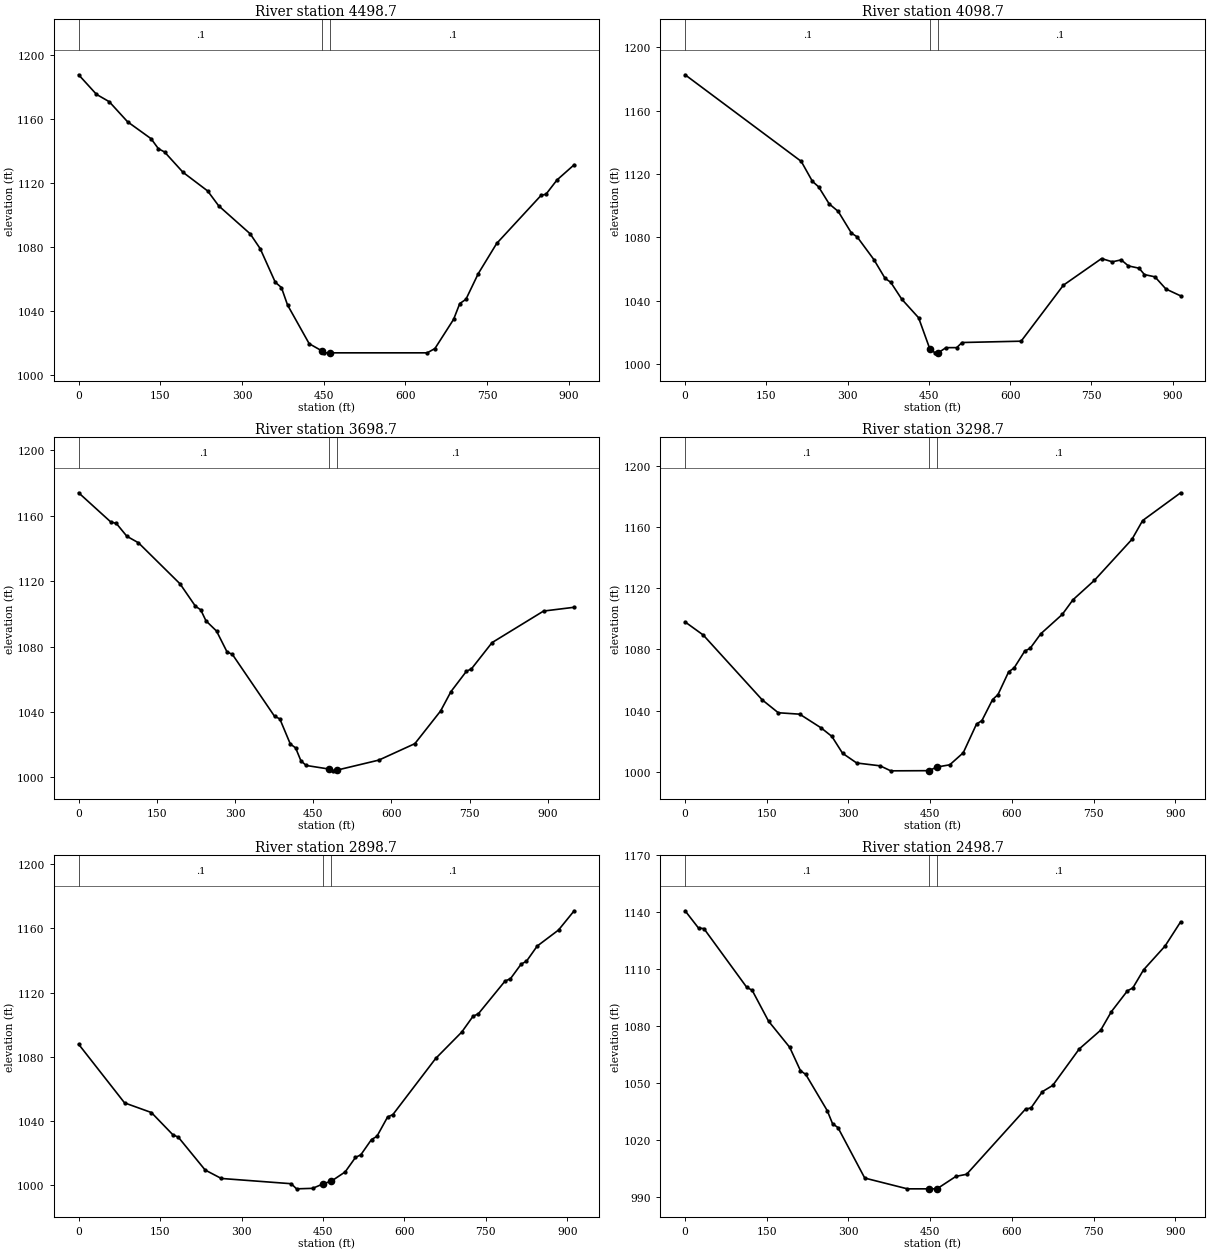
Type RM Length L Ch R = 1 ,4498.7  ,395.156,400,409.235
XS GIS Cut Line= 3
     1721637.214      350661.099     1721240.797      350884.434
      1720844.38      351107.769
#Sta/Elev= 30
       0 1187.52    32.8 1175.28    56.2  1170.7      90 1158.12     133 1147.59
   146.5 1141.33   157.8 1139.28   191.7 1126.58   236.9 1114.94   257.2 1105.64
     315 1088.16   333.5 1078.82   361.1  1057.9   372.4 1054.59   383.7 1043.62
   423.4 1019.48   447.5 1014.86   451.5 1013.78   462.5 1013.78   640.1 1013.78
   654.3 1016.47   688.6 1034.71   699.9 1044.58   711.2 1047.21   733.8 1063.23
   767.7 1082.13   849.6  1112.3   858.1 1112.82   878.5 1121.81     910  1131.3
#Mann= 3 , 0 , 0
       0      .1       0   447.5    .045       0   462.5      .1       0
Bank Sta=447.5,462.5
XS Rating Curve= 0 ,0
Exp/Cntr=0.3,0.1

Type RM Length L Ch R = 1 ,4098.7  ,401.858,400,398.775
XS GIS Cut Line= 3
     1721487.672      350405.126      1721049.27      350543.533
     1720596.939      350594.281
#Sta/Elev= 30
       0 1182.53   214.4 1127.94     235 1115.38   246.5 1111.87     266 1101.14
   282.7 1096.39   307.2 1082.68   317.6 1080.35   348.5 1066.04   369.2 1054.18
   379.5 1051.77   400.1 1041.02   431.1 1029.34   452.2 1009.35   461.9 1007.22
   467.2 1007.22   481.7 1010.49   501.5  1010.5   511.3 1013.73   620.4 1014.57
   698.4 1049.86   768.9 1066.66   788.7 1064.61   805.2 1065.84   818.4 1062.04
   838.2 1060.57   848.1 1056.55   867.5 1055.14   887.7 1047.47   914.9 1043.14
#Mann= 3 , 0 , 0
       0      .1       0   452.2    .045       0   467.2      .1       0
Bank Sta=452.2,467.2
XS Rating Curve= 0 ,0
Exp/Cntr=0.3,0.1

Type RM Length L Ch R = 1 ,3698.7  ,387.43,400,404.632
XS GIS Cut Line= 3
     1721471.669      350278.688      1720996.79      350165.579
     1720535.883      350127.604
#Sta/Elev= 30
       0 1174.07    61.7  1156.2    72.3 1155.33    92.5 1147.47   114.8 1143.46
   194.5 1118.36     224 1104.68   234.2 1102.45   244.3 1095.71   264.5 1089.48
   284.7 1076.69   294.9 1075.21   375.8 1037.32   385.9 1035.74   406.1 1020.34
   416.2 1017.99   426.4 1010.09   436.5 1007.22   480.7 1005.01   487.3 1003.93
   495.7 1004.38   575.9  1010.5     645 1020.57   694.4 1040.58   714.2 1052.39
   743.8 1064.81   753.6 1066.36   793.1  1082.4   891.9  1101.7   950.6 1104.01
#Mann= 3 , 0 , 0
       0      .1       0   480.7    .045       0   495.7      .1       0
Bank Sta=480.7,495.7
XS Rating Curve= 0 ,0
Exp/Cntr=0.3,0.1

Type RM Length L Ch R = 1 ,3298.7  ,397.646,400,399.799
XS GIS Cut Line= 3
     1721454.337      349847.931     1720999.343      349846.636
     1720544.352      349841.275
#Sta/Elev= 30
       0 1097.97    33.3 1089.42   141.6 1047.04   171.1 1038.62   210.5 1037.68
   249.8 1028.72   269.5 1023.17   289.2 1012.12   315.1 1005.78   358.1 1003.93
   377.7 1000.65   447.5 1000.76   462.5 1003.14     486 1004.59   510.8 1012.46
   535.2 1031.25     545 1033.45   564.7 1047.24   574.5 1050.42   594.2 1065.39
   604.1 1067.85   623.8 1078.96   633.6 1080.69   653.3 1090.27   692.6 1102.87
   712.3 1112.45   751.7 1125.17   820.6 1151.95   840.2 1164.22     910 1182.38
#Mann= 3 , 0 , 0
       0      .1       0   447.5    .045       0   462.5      .1       0
Bank Sta=447.5,462.5
XS Rating Curve= 0 ,0
Exp/Cntr=0.3,0.1

Type RM Length L Ch R = 1 ,2898.7  ,403.238,400,399.116
XS GIS Cut Line= 3
     1721455.873      349495.604     1721000.481      349446.638
     1720546.016      349445.344
#Sta/Elev= 30
       0 1087.73    84.6 1051.11     134 1045.08   173.6 1031.19   183.5 1029.73
     233 1009.19   262.7 1003.93   391.4 1000.65   401.3  997.45   430.9  997.76
   450.5 1000.61   465.5 1002.28   490.8 1008.01   509.8 1017.06   519.7 1018.72
   539.3 1028.25   549.2 1030.18   568.9 1042.29   578.7 1043.82   657.4 1078.82
   705.4 1095.29   726.3  1105.2   736.1 1106.75   785.3 1127.19   795.2 1128.64
   814.9 1137.76   824.7 1139.55   844.4    1149   883.7 1159.03   912.5 1171.04
#Mann= 3 , 0 , 0
       0      .1       0   450.5    .045       0   465.5      .1       0
Bank Sta=450.5,465.5
XS Rating Curve= 0 ,0
Exp/Cntr=0.3,0.1

Type RM Length L Ch R = 1 ,2498.7  ,389.13,400,410.87
XS GIS Cut Line= 3
     1721514.548      349038.772     1721059.838      349055.011
     1720605.127      349071.251
#Sta/Elev= 30
       0 1140.72    24.7 1131.58    34.5 1131.34   113.3 1100.32   123.1 1098.83
   153.2 1082.54   192.1 1068.72   211.8 1056.43   221.6 1054.41     261 1035.34
   270.8 1028.44   280.7 1026.39   329.9  999.77   408.2  994.09   447.5  994.09
   462.5  994.09   497.3 1000.65     517 1001.77   625.3  1036.2   635.2 1036.74
   656.1 1045.34   675.1 1048.63   723.8 1067.86   763.2 1077.76   782.8 1087.52
   812.4 1098.55   822.2 1100.03   841.9 1109.57   881.3 1122.09     910 1134.89
#Mann= 3 , 0 , 0
       0      .1       0   447.5    .045       0   462.5      .1       0
Bank Sta=447.5,462.5
XS Rating Curve= 0 ,0
Exp/Cntr=0.3,0.1

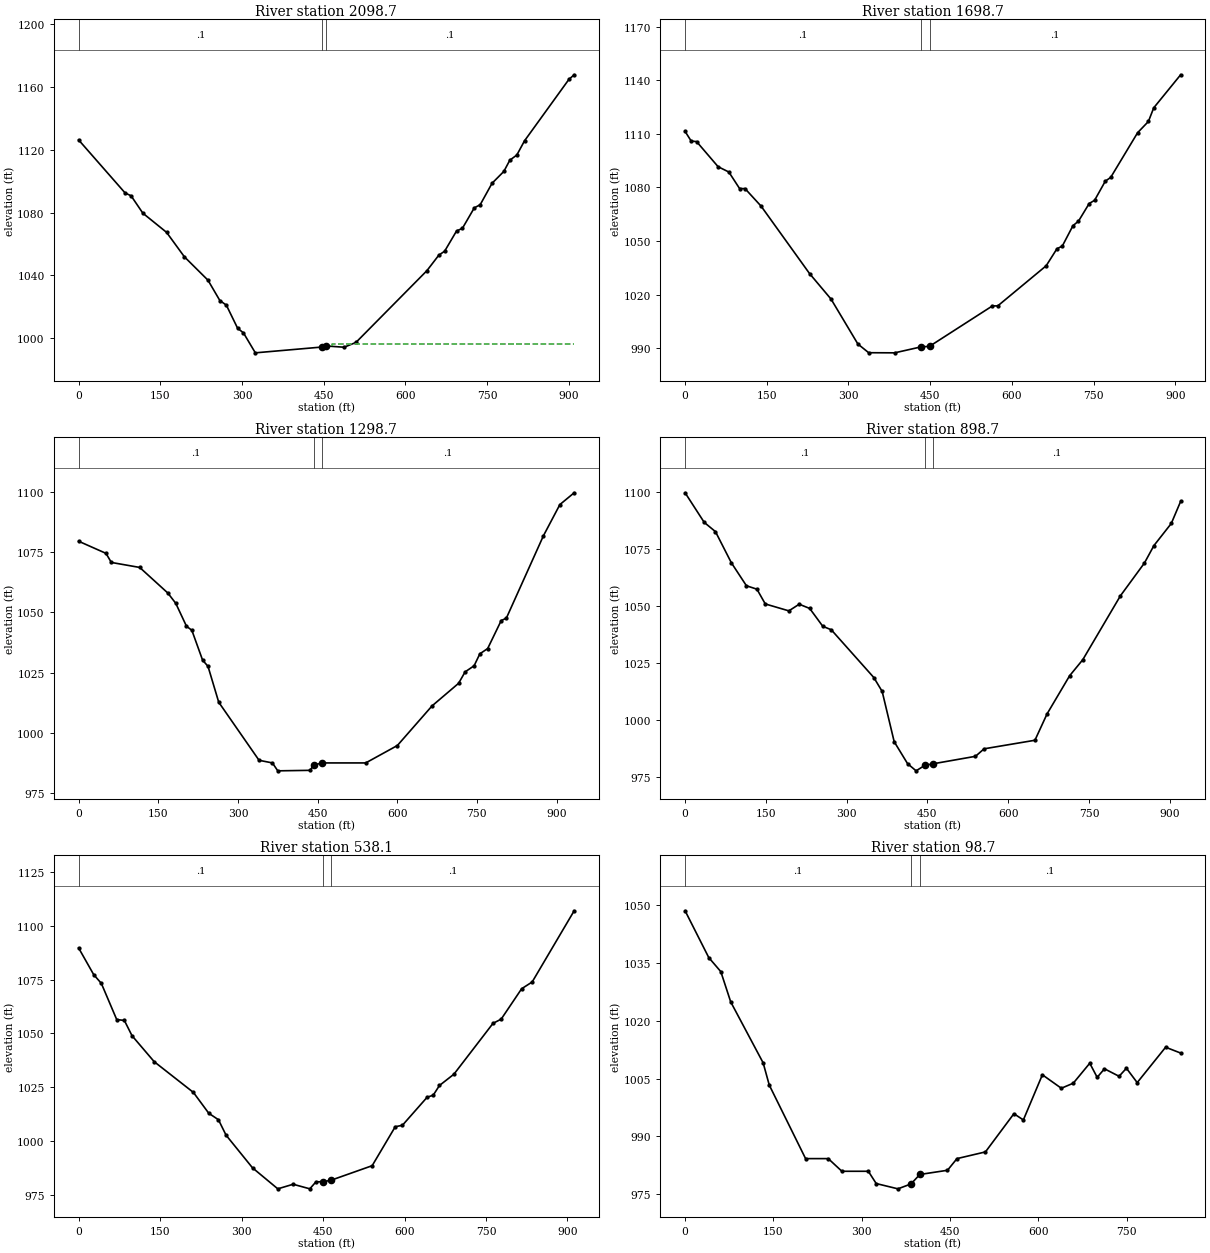
Type RM Length L Ch R = 1 ,2098.7  ,408.022,400,391.978
XS GIS Cut Line= 3
     1721537.671      348864.736     1721125.687      348671.618
     1720713.703      348478.501
#Sta/Elev= 30
       0 1126.21    85.4 1092.47    96.3 1090.69     118 1079.61   161.5 1067.44
   194.1 1051.93   237.5 1037.02   259.3 1024.09   271.3 1021.13   291.9 1006.49
   302.7 1003.49   324.5  990.81   447.5  994.52   454.9  995.17   487.5  994.38
   509.2  997.41   639.6 1043.08   661.4 1052.91   672.2 1055.48     694 1068.31
   704.8 1070.03   726.6 1083.03   737.4    1085   759.2 1098.65   780.9 1106.21
   791.8 1113.31   804.7 1116.62   818.8 1125.64   900.4 1164.75     910 1167.65
#Mann= 3 , 0 , 0
       0      .1       0   447.5    .045       0   454.9      .1       0
#XS Ineff= 2 , 0
                          465.97          996.29
Permanent Ineff=
       F       F
Bank Sta=447.5,454.9
XS Rating Curve= 0 ,0
Exp/Cntr=0.3,0.1

Type RM Length L Ch R = 1 ,1698.7  ,396.719,400,393.656
XS GIS Cut Line= 3
     1721707.669      348337.266     1721254.331      348298.409
     1720800.993      348259.551
#Sta/Elev= 30
       0 1111.36    11.2 1105.96    21.1 1105.67    60.6 1091.63    80.3 1088.66
   100.1 1079.39     110 1079.39   139.6 1069.55   228.5 1031.87     268 1017.58
   317.3  992.45   337.1   987.6   384.8  987.53   432.5  990.81   448.8  991.17
   564.3 1013.78   574.1 1013.78     663 1036.22   682.8 1045.75   692.6 1047.23
   712.2 1058.66   722.3 1061.16     742 1071.05   751.9 1072.83   771.6 1083.55
   781.5 1085.65   830.9 1110.64   850.7 1116.92   860.5 1124.55   909.9 1143.04
#Mann= 3 , 0 , 0
       0      .1       0   432.5    .045       0   448.8      .1       0
Bank Sta=432.5,448.8
XS Rating Curve= 0 ,0
Exp/Cntr=0.3,0.1

Type RM Length L Ch R = 1 ,1298.7  ,427.357,400,385.998
XS GIS Cut Line= 3
     1721736.799       348004.58     1721298.721      347901.503
     1720822.849      347984.738
#Sta/Elev= 30
       0 1079.49    51.5 1074.46    61.6 1070.69     115 1068.62   167.9 1058.02
   182.9 1053.74   203.1 1044.23   213.2 1042.55   233.4 1030.18   243.6  1027.6
   263.8 1012.71   339.7  988.63   364.9  987.53     375  984.25   435.6  984.46
   442.5  986.55   457.5  987.53   540.6  987.53   600.2  994.76   665.5 1011.19
   715.5 1020.56   727.7 1025.29   744.7 1027.84   755.5 1032.79   770.2 1034.97
   795.7 1046.58   805.4 1047.58   875.3  1081.8   906.2  1094.7   933.1 1099.59
#Mann= 3 , 0 , 0
       0      .1       0   442.5    .045       0   457.5      .1       0
Bank Sta=442.5,457.5
XS Rating Curve= 0 ,0
Exp/Cntr=0.3,0.1

Type RM Length L Ch R = 1 ,898.7   ,364.152,360.527,352.092
XS GIS Cut Line= 3
     1721423.296      347244.852     1721140.436      347598.427
     1720778.542      347894.355
#Sta/Elev= 30
       0 1099.47    35.5 1086.53    56.4 1082.48    85.9 1068.87   113.9 1058.82
   133.4 1057.32   148.9 1050.87   192.7 1047.84   211.9 1050.75   231.4  1048.9
   255.7  1041.1   271.5 1039.57   350.5 1018.69     366 1012.61   388.3  990.64
   413.2  981.03     429   977.9   445.3  980.31   460.3  980.97   539.3  984.25
   555.3  987.53   649.7  991.27   672.2 1002.78   714.1 1019.46   738.6  1026.5
   808.5 1054.44     853 1068.74   870.7 1076.39   902.9 1086.04   920.3  1095.7
#Mann= 3 , 0 , 0
       0      .1       0   445.3    .045       0   460.3      .1       0
Bank Sta=445.3,460.3
XS Rating Curve= 0 ,0
Exp/Cntr=0.3,0.1

Type RM Length L Ch R = 1 ,538.1   ,422.228,439.473,448.447
XS GIS Cut Line= 3
     1721184.454      347026.213     1720888.337      347331.122
     1720644.476      347752.935
#Sta/Elev= 30
       0 1089.75    27.7 1077.37    41.8 1073.28    70.1 1056.46    84.2 1056.03
    98.3 1048.93   139.1 1036.85   211.3 1022.55   239.6 1012.85   257.4 1009.84
   271.4 1002.67   320.1  987.46   366.7  977.69   394.9  979.82   425.6   977.7
     437  980.97   450.1  980.97   465.1  981.73   540.4  988.46   582.9 1006.59
   596.1 1007.26   641.5 1020.28   652.9 1021.29   664.3 1025.78   690.9 1031.02
   762.9 1054.69   777.9 1056.64   815.6 1070.79     835 1073.94   912.3 1107.06
#Mann= 3 , 0 , 0
       0      .1       0   450.1    .045       0   465.1      .1       0
Bank Sta=450.1,465.1
XS Rating Curve= 0 ,0
Exp/Cntr=0.3,0.1

Type RM Length L Ch R = 1 ,98.7    ,101.671,98.675,103.95
XS GIS Cut Line= 3
     1720967.426      346909.309     1720592.903      347022.809
     1720235.845      347298.168
#Sta/Elev= 30
       0 1048.46    40.2 1036.34    60.7 1032.69    77.5 1024.85   132.6 1009.06
     143  1003.3   204.7  984.25   243.2  984.25   266.4  980.97   311.3  980.97
   324.7  977.79   361.6  976.42   383.8  977.69   398.8  980.14   445.8  981.23
   461.9  984.25   510.3  985.99   558.6  995.88   574.7  994.27     607 1005.97
   639.2 1002.48   659.5 1003.79   687.5 1008.96   700.1 1005.31   712.5 1007.52
   737.3 1005.58   749.8 1007.66   768.1 1003.94   816.4 1013.11   841.9  1011.6
#Mann= 3 , 0 , 0
       0      .1       0   383.8    .045       0   398.8      .1       0
Bank Sta=383.8,398.8
XS Rating Curve= 0 ,0
Exp/Cntr=0.3,0.1

Chan Stop Cuts=-1
Use User Specified Reach Order=0